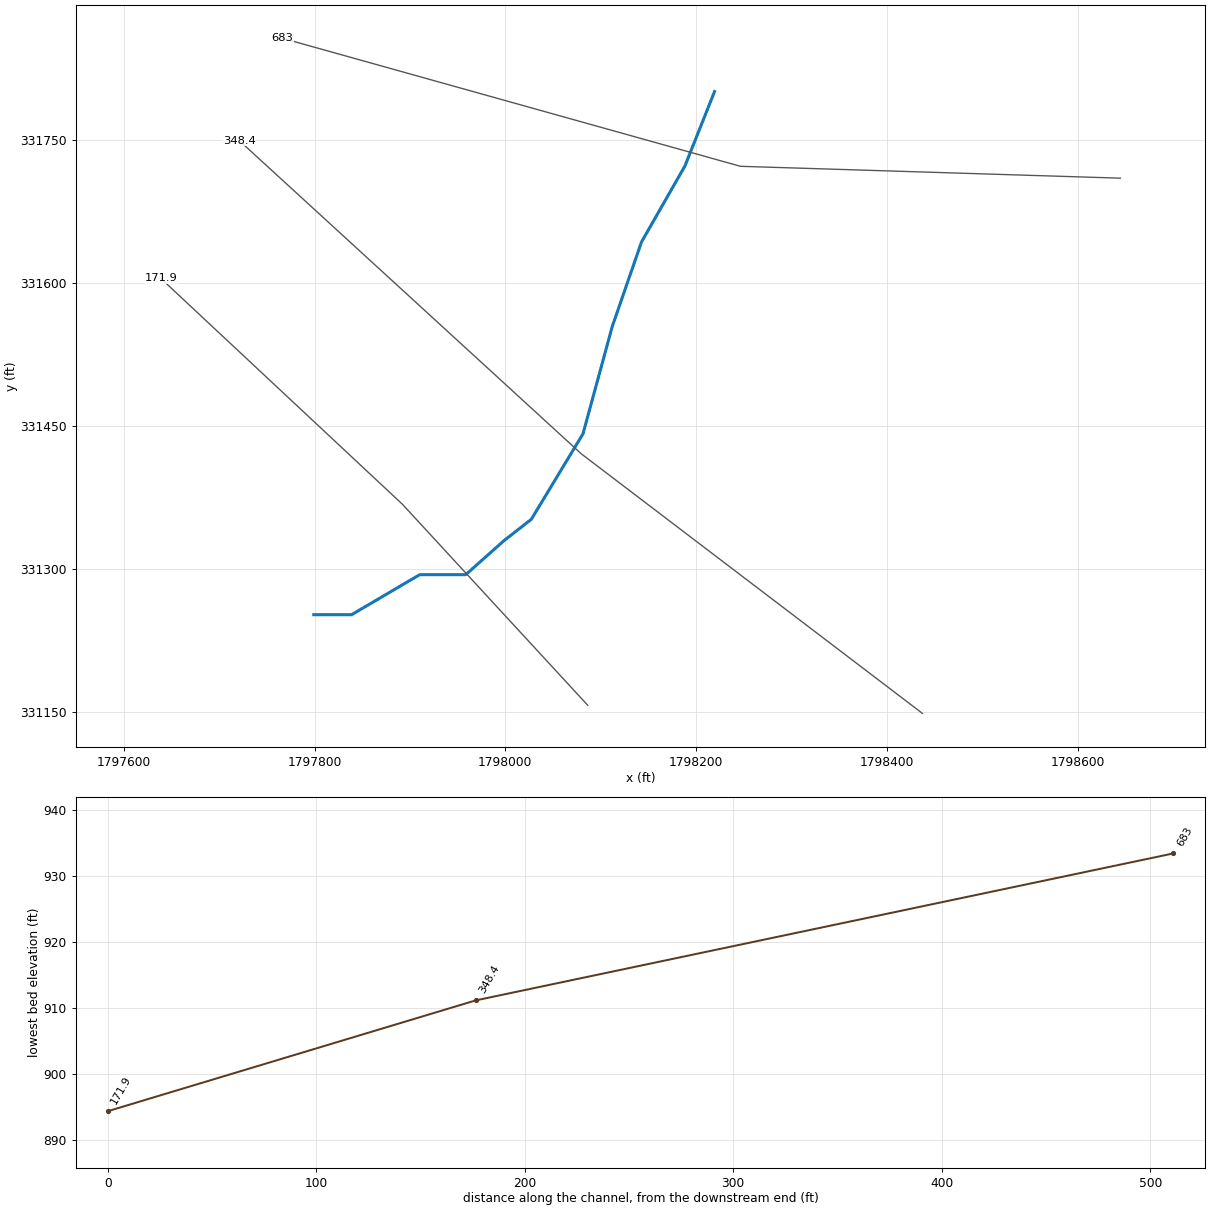
--- NP4.prj (project) ---

Proj Title=NP4
Current Plan=p01
Default Exp/Contr=0,0
English Units
Geom File=g01
Flow File=f01
Plan File=p01
BEGIN DESCRIPTION:
END DESCRIPTION:
DSS Export Rating Curves= 0
DSS Export Rating Curve Sorted= 0
DSS Export Volume Flow Curves= 0
DXF OffsetX= 0
DXF OffsetY= 0
DXF ScaleX= 0
DXF ScaleY= 0

--- NP4.p01 (plan) ---

Plan Title=Floodplain
Program Version=4.00
Geom File=g01
Flow File=f01
K Sum by GR=0
Std Step Tol=0.01
Critical Tol=0.01
Num of Std Step Trials=20
Max Error Tol=0.3
Flow Tol Ratio=0.001
Split Flow NTrial=30
Split Flow Tol=0.02
Split Flow Ratio=0.02
Log Output Level=0
Friction Slope Method=1
Unsteady Friction Slope Method=2
Unsteady Bridges Friction Slope Method=1
Global Log Level=0
CheckData=False
Run HTab=0
Run UNet=0
Run PostProcess=0
UNET Theta=0
UNET Theta Warmup=0
UNET ZTol=0
UNET ZSATol=0
UNET MxIter=0
UNET MaxInSteps=0
UNET DtIC=0
UNET DtMin=0
UNET MaxCRTS=0
UNET WFStab=0
UNET SFStab=0
UNET WFX=0
UNET SFX=0
UNET DSS MLevel=0
UNET DZMax Abort=0
UNET Convert EG Bridges=0
UNET Use Existing IB Tables=0
UNET Froude Limit=0
UNET Froude Power=0
Write IC File=0
Echo Input=False
Echo Output=False
Write Detailed=0

--- NP4.f01 (steady flow) ---

Flow Title=NFF Regression Equation
Program Version=4.00
Number of Profiles=1
Profile Names=P100yr
River Rch & RM=NP4,Main      ,683
816.4711
River Rch & RM=NP4,Main      ,348.4
820.4076
Boundary for River Rch & Prof#=NP4,Main      ,1
Up Type=0
Dn Type=3
Dn Slope=0.066263

--- NP4.g01 (geometry) ---

Geom Title=USGS 3m DEM
Program Version=4.00

River Reach=NP4             ,Main
Reach XY= 11
     1798219.306      331800.457     1798188.252      331722.422
     1798142.792      331642.868     1798112.107      331554.222
     1798081.422       331441.71      1798027.26      331352.051
     1797998.676       331329.72      1797958.48       331293.99
     1797910.245       331293.99     1797838.786      331252.007
     1797799.182      331252.007

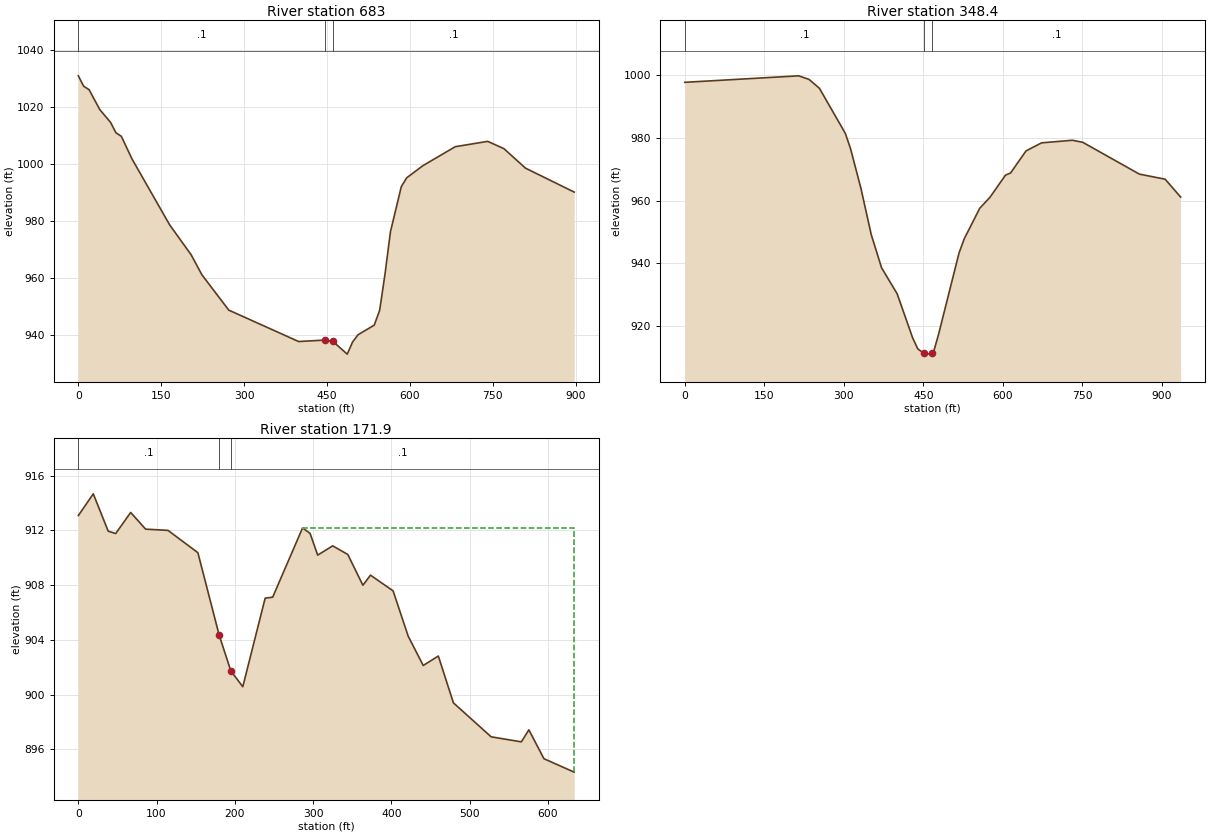
Type RM Length L Ch R = 1 ,683     ,344.025,334.612,323.961
XS GIS Cut Line= 3
     1798644.812      331709.666     1798246.511      331722.113
     1797766.533      331856.275
#Sta/Elev= 30
       0 1031.04     9.7 1027.38    19.4 1026.19    38.9 1019.17    58.3 1014.71
      68 1011.06    77.8 1009.81    97.2 1001.83   165.2  978.74   204.1  968.22
   223.5  961.23   272.1  948.82   398.5  937.79   445.5  938.29   460.5  937.83
   486.4  933.37   496.2  937.66     506  940.17   535.3  943.55   545.1  948.76
   554.8  961.52   564.6  976.33   584.2  992.12   593.9  995.23   623.3  999.51
   681.9 1006.17   740.5 1008.04   769.8 1005.49   808.9  998.64   896.9  990.24
#Mann= 3 , 0 , 0
       0      .1       0   445.5    .045       0   460.5      .1       0
Bank Sta=445.5,460.5
XS Rating Curve= 0 ,0
Exp/Cntr=0.3,0.1

Type RM Length L Ch R = 1 ,348.4   ,179.697,176.523,177.385
XS GIS Cut Line= 3
     1798437.262      331148.541     1798079.521      331420.737
     1797721.076      331749.005
#Sta/Elev= 30
       0  997.64     215  999.71   234.5  998.57   254.1  995.73   302.9  981.39
   312.7  976.56   332.3  963.93   351.8  949.18   371.3   938.6   400.7  930.33
     430  916.27   439.7  912.79   451.4  911.34   459.2  911.12   466.4  911.45
     469  911.57   478.7  917.32   517.6  943.39   527.3  947.82   556.5  957.54
   575.9  961.06   605.1  968.09   614.8   968.8   643.9  975.81   673.1  978.37
   731.4   979.2   750.9  978.55   857.8  968.42   906.4   966.8   935.6  961.13
#Mann= 3 , 0 , 0
       0      .1       0   451.4    .045       0   466.4      .1       0
Bank Sta=451.4,466.4
XS Rating Curve= 0 ,0
Exp/Cntr=0.3,0.1

Type RM Length L Ch R = 1 ,171.9   ,189.428,171.911,151.598
XS GIS Cut Line= 3
     1798086.408      331156.981      1797892.16      331367.691
     1797638.649      331604.739
#Sta/Elev= 30
       0  913.08    19.1  914.67    38.2  911.94    47.8  911.77    66.9  913.31
      86  912.09   114.6     912   152.8  910.37   179.9  904.37   194.9  901.73
   210.2  900.58   238.8  907.05   248.4  907.12   286.6  912.18   296.2  911.78
   305.9  910.19   325.1  910.87   344.4  910.24   363.7  907.99   373.4  908.73
   402.3  907.58   421.6  904.27   440.8  902.13   460.1  902.82   479.4   899.4
   527.6  896.92   566.2  896.55   575.8  897.43   595.1  895.32   633.7  894.34
#Mann= 3 , 0 , 0
       0      .1       0   179.9    .045       0   194.9      .1       0
#XS Ineff= 2 , 0
                          286.45          912.21
Permanent Ineff=
       F       F
Bank Sta=179.9,194.9
XS Rating Curve= 0 ,0
Exp/Cntr=0.3,0.1

Chan Stop Cuts=-1
Use User Specified Reach Order=0